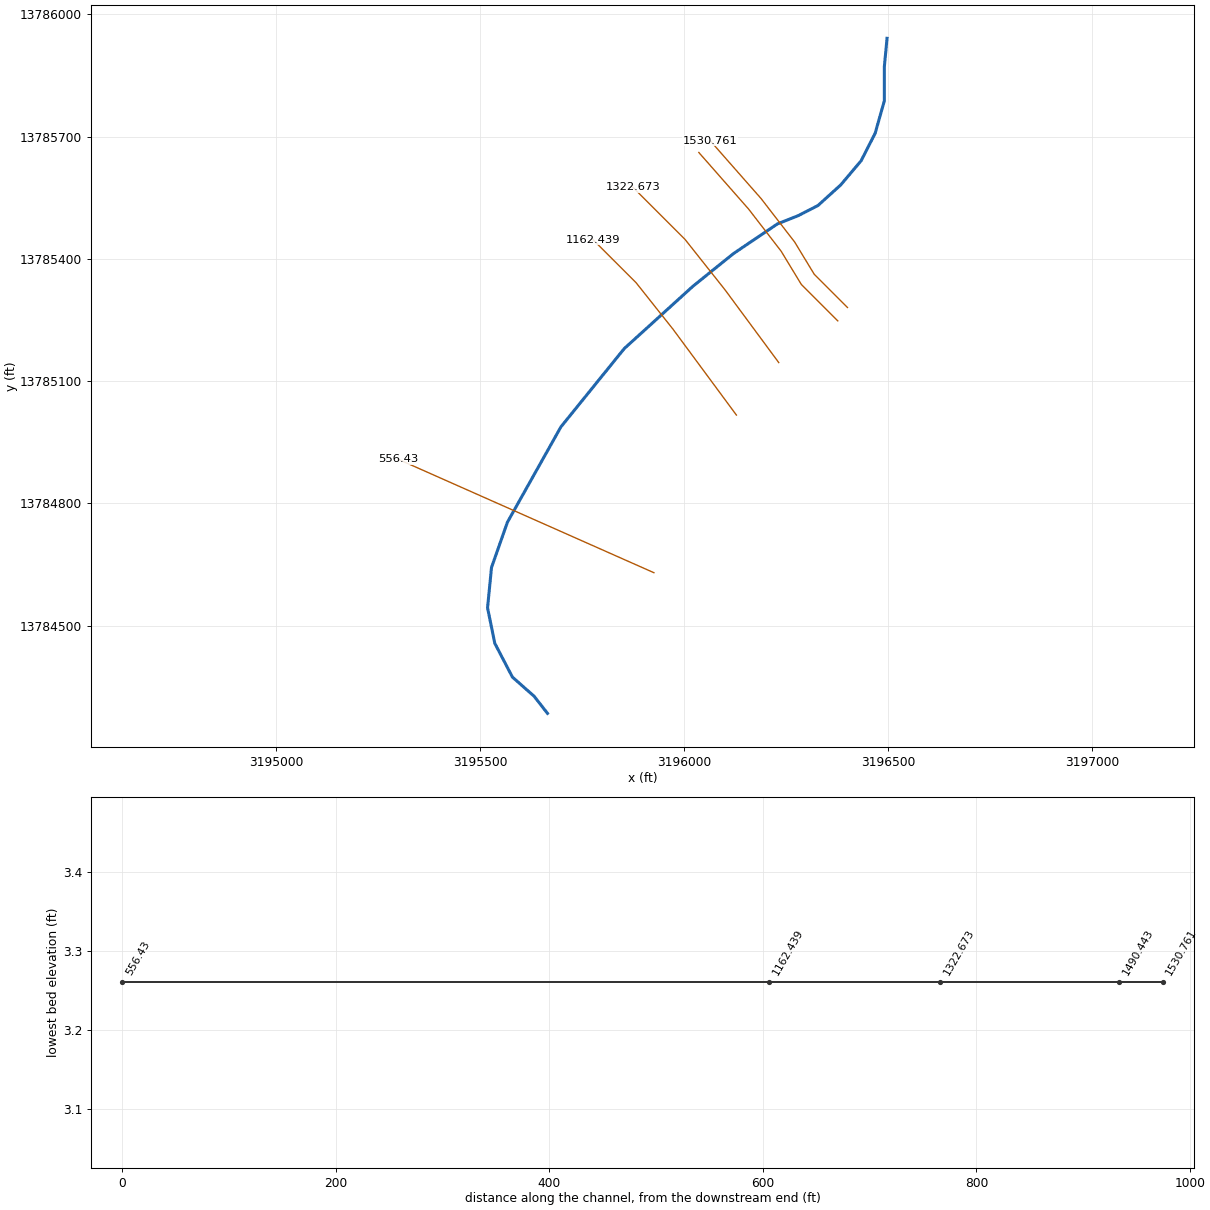
--- B204_04_00.prj (project) ---

Proj Title=B204-04-00
Current Plan=p04
Default Exp/Contr=.3,.1
English Units
Geom File=g01
Geom File=g02
Flow File=f04
Flow File=f05
Plan File=p04
Plan File=p05
Y Axis Title=Elevation
X Axis Title(PF)=Main Channel Distance
X Axis Title(XS)=Station
BEGIN DESCRIPTION:
Armand Bayou
Horsepen Bayou Diversion Channel
HCFCD Unit B204-04-00
Flood Hazard Model
10, 2, 1, 0.2% Event
Filename B204_04_00.prj
Prepared by: Christopher Moss DATE: 6/15/2004
Reviewed by:                           DATE:
STATUS FINAL
END DESCRIPTION:
DSS File=dss
DSS Export Rating Curves= 0
DSS Export Rating Curve Sorted= 0
DSS Export Volume Flow Curves= 0
DXF OffsetX= 0
DXF OffsetY= 0
DXF ScaleX= 1
DXF ScaleY= 10

--- B204_04_00.p04 (plan) ---

Plan Title=FEMA Effective June 2007
Version=Version 3.0.1  Mar 2001
Short Identifier=FEMAeff0607
Geom File=g01
Flow File=f04
Subcritical Flow
K Sum by GR= 0
Std Step Tol= 0.01
Critical Tol= 0.01
Num of Std Step Trials= 20
Max Error Tol= 0.3
Flow Tol Ratio= 0.001
Split Flow NTrial= 30
Split Flow Tol= 0.02
Split Flow Ratio= 0.02
Log Output Level= 0
Friction Slope Method= 0
Unsteady Friction Slope Method= 2
Secant Critical Depth
Global Vel Dist= 0 , 0 , 0
Global Log Level= 0
CheckData=True
Encroach Param=-1 ,0,0, 0
Computation Interval=1HOUR
Output Interval=1HOUR
Run HTab= 0
Run UNet= 0
Run PostProcess= 0
UNET Theta= 1
UNET ZTol= 0.02
UNET ZSATol= 0.1
UNET MxIter= 20
UNET MaxInSteps= 20
UNET DtIC= 0
UNET DtMin= 0
UNET MaxCRTS= 20
UNET WFStab= 2
UNET SFStab= 1
UNET WFX= 1
UNET SFX= 1
UNET Convert EG Bridges=-1
UNET Use Existing IB Tables=-1
Instantaneous Interval=1HOUR
DSS File=dss
Write IC File= 0
IC Time=0
Write Velocity= 0
Write Detailed= 0

--- B204_04_00.p05 (plan) ---

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Plan Title=Floodway
Short Identifier=Floodway0607
Geom File=g02
Flow File=f05
Encroach Param=-1 ,0,0, 2
Encroach River=B204-04-00
Encroach Reach=MAIN
Encroach Node=1530.761
       1 4934.65 5065.35
Encroach Node=1490.443
       1 4934.65 5065.35
Encroach Node=1406.6
       1 4929.65 5060.35
Encroach Node=1322.673
       1 4929.65 5060.35
Encroach Node=1162.439
       1    4946    5045
Encroach Node=556.43
       1 4934.65 5065.35
Encroach Reach=B204-04-00_0006
Encroach Node=1530.761
       1 4934.65 5065.35
Encroach Node=1490.443
       1 4934.65 5065.35
Encroach Node=1406.6
       1 4929.65 5060.35
Encroach Node=1322.673
       1 4929.65 5060.35
Encroach Node=1162.439
       1    4946    5045
Encroach Node=556.43
       1 4934.65 5065.35

--- B204_04_00.f04 (steady flow) ---

Flow Title=FEMA Effective June 2007
Version=Version 3.0.1  Mar 2001
Number of Profiles= 4
Profile Names=10PCT_10yr, 2PCT_50yr, 1PCT_100yr, 0.2PCT_500yr
River Rch & RM=Diversion Channe,Diversion       ,1530.761
     637     861     988    1407
River Rch & RM=B204-04-00,B204-04-00_0006            ,1530.761
     637     861     988    1407
Boundary for River Rch & Prof#=B204-04-00,B204-04-00_0006            , 1
Up Type= 0
Dn Type= 3
Dn Slope=.0016
DSS Import GetInterval= 0
DSS Import GetPeak= 0
DSS Import FillOption= 0

--- B204_04_00.f05 (steady flow) ---

Flow Title=Floodway
Version=Version 3.0.1  Mar 2001
Number of Profiles= 2
Profile Names=1PCT_100yr, 1PCTFloodway_100yrFW
River Rch & RM=B204-04-00,B204-04-00_0006            ,1530.761
     988     988
Boundary for River Rch & Prof#=B204-04-00,B204-04-00_0006            , 1
Up Type= 0
Dn Type= 3
Dn Slope=.0016
DSS Import GetInterval= 0
DSS Import GetPeak= 0
DSS Import FillOption= 0

--- B204_04_00.g01 (geometry) ---

Geom Title=B204-04-00 June 2007
Program Version=3.11

River Reach=B204-04-00      ,B204-04-00_0006
Reach XY= 30
     3196497.337    13785941.137      3196495.12    13785917.646
     3196490.721     13785871.01     3196490.721    13785787.652
     3196468.228    13785708.264     3196433.826    13785640.784
     3196383.547    13785581.243     3196327.975    13785530.963
     3196279.019    13785505.824     3196228.739    13785485.977
     3196184.701    13785456.216      3196120.75       13785413.
       3196021.5       13785333.     3196006.519    13785319.398
     3195943.627     13785262.29        3195853.       13785180.
     3195820.659    13785140.003     3195813.259    13785130.853
     3195809.162    13785125.785     3195768.587    13785075.606
     3195755.946    13785059.971     3195748.935    13785051.302
      3195697.75       13784988.       3195566.5       13784754.
       3195527.5       13784643.      3195517.75       13784544.
       3195535.5       13784457.      3195578.75       13784374.
        3195632.       13784327.      3195664.75       13784285.

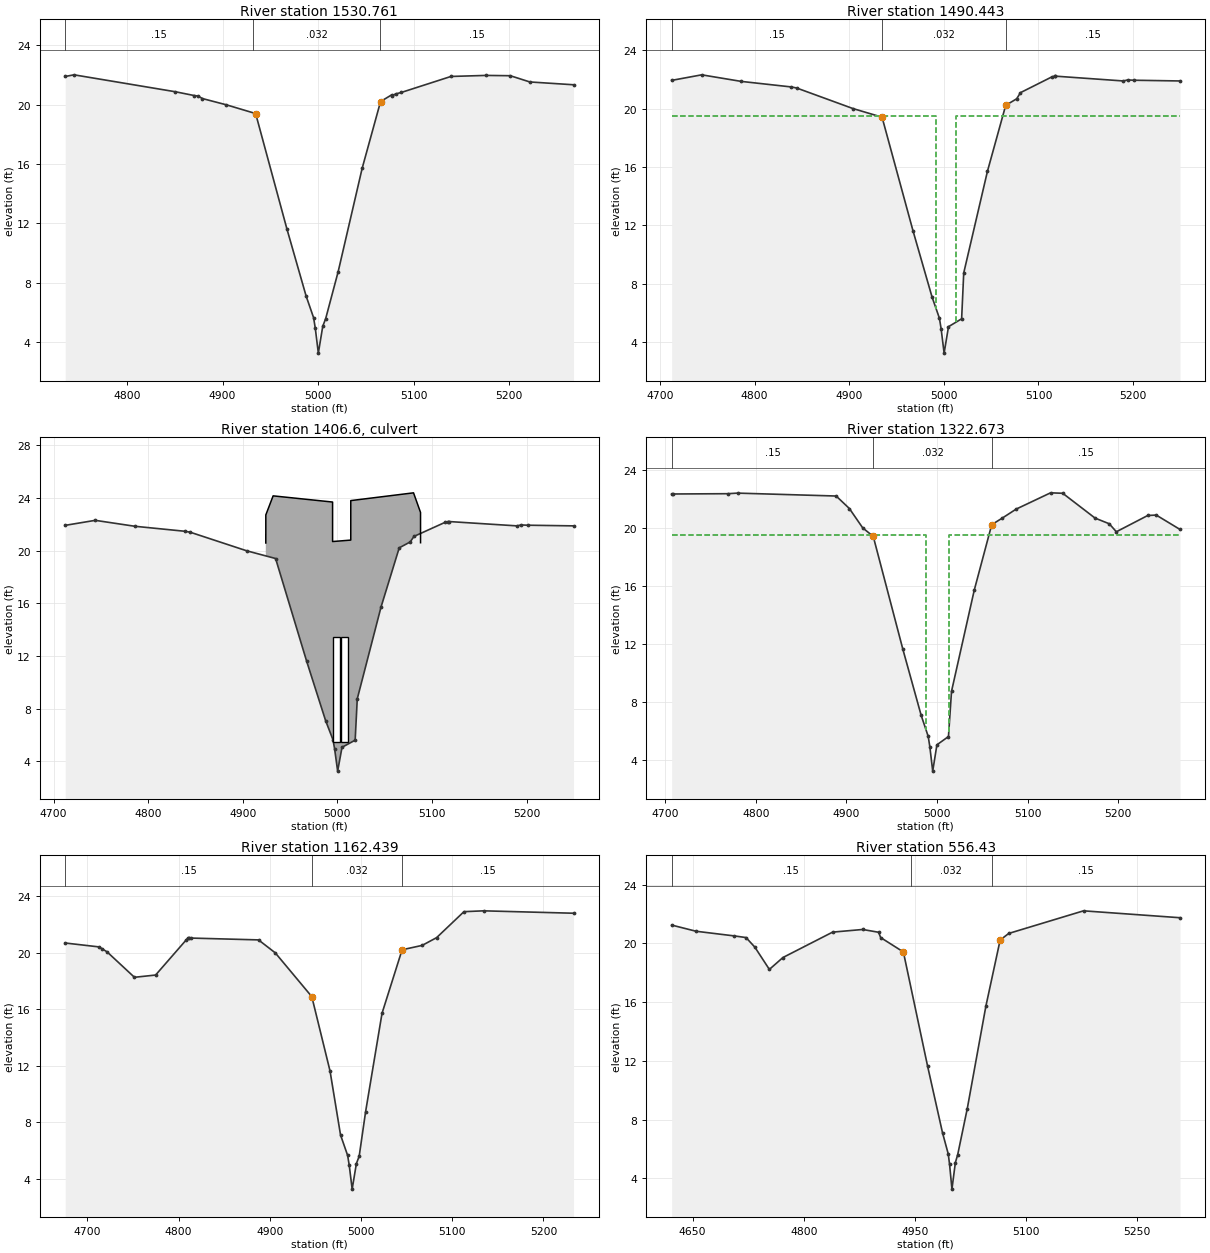
Type RM Length L Ch R = 1 ,1530.761,40.3,40.32,40.32
XS GIS Cut Line= 5
     3196400.333     13785280.75     3196318.879    13785362.204
     3196270.752    13785441.528     3196188.726    13785547.765
     3196063.537     13785690.17
#Sta/Elev= 27
 4735.43   21.91  4744.7   22.02 4850.62   20.88 4870.69   20.62 4874.42   20.59
    4879   20.42 4903.95      20 4934.65   19.41 4967.38   11.63  4987.5     7.1
 4995.28    5.65 4997.06    4.94 5000.25    3.26 5004.88    5.07 5007.95    5.59
 5020.99    8.75  5046.1   15.72 5065.35   20.22 5076.96   20.67 5077.77   20.61
 5080.98   20.73 5086.97   20.83 5138.97   21.91 5175.41   21.98 5201.05   21.96
 5221.47   21.54 5267.23   21.35
#Mann= 3 ,-1 , 0
 4735.43     .15       0  4932.2    .032       0 5065.15     .15       0
Bank Sta=4934.65,5065.35
XS Rating Curve= 0
Exp/Cntr=0.5,0.3

Type RM Length L Ch R = 1 ,1490.443,163.59,167.77,167.13
XS GIS Cut Line= 5
     3196376.638    13785247.876     3196287.184    13785337.331
     3196237.719     13785418.86     3196157.843    13785522.311
     3196035.859    13785661.071
#Sta/Elev= 26
 4712.27   21.93 4744.03   22.31 4785.82   21.86 4838.78   21.48 4844.31   21.41
 4903.95      20 4934.65   19.41 4967.38   11.63  4987.5     7.1 4995.28    5.65
 4997.06    4.94 5000.25    3.26 5004.88    5.07 5018.77    5.61 5020.99    8.75
  5046.1   15.72 5065.35   20.22 5076.96   20.67 5080.98   21.09 5113.87   22.16
 5117.09   22.22 5117.68   22.22 5189.72   21.89 5194.24   21.96 5200.97   21.94
 5249.59   21.89
#Mann= 3 ,-1 , 0
 4712.27     .15       0 4934.65    .032       0 5065.35     .15       0
#XS Ineff= 2 , 0
       0    4992    19.5    5013       0    19.5
Permanent Ineff=
       F       F
Bank Sta=4934.65,5065.35
XS Rating Curve= 0
Exp/Cntr=0.5,0.3

Type RM Length L Ch R = 2 ,1406.6  ,,,
BEGIN DESCRIPTION:
Garden Creek Way
END DESCRIPTION:
Bridge Culvert--1,0,-1,-1, 0
Deck Dist Width WeirC Skew NumUp NumDn MinLoCord MaxHiCord MaxSubmerge Is_Ogee
55,40,2.6,0, 10, 10, , , 0.95, 0, 0,0,,
  4924.3 4924.31 4932.04  4994.9 4994.91 5014.11 5014.12 5080.46 5087.87 5087.88
   20.59   22.72   24.17    23.7    20.7   20.81   23.81    24.4   22.91   20.61
                                                                                
  4924.3 4924.31 4932.04  4994.9 4994.91 5014.11 5014.12 5080.46 5087.87 5087.88
   20.59   22.72   24.17    23.7    20.7   20.81   23.81    24.4   22.91   20.61
                                                                                
Multiple Barrel Culv=2,8,7,65,0.012,0.2,1,8,1,5.4409,5.4409, 2,Culvert #1  , 0 ,55
 4998.94 4992.94 5007.52 5002.52
Culvert Bottom n=0.012
BC Design=,, 0 ,, 0 ,,,,,,
BC HTab HWMax=22.31

Type RM Length L Ch R = 1 ,1322.673,160.61,160.23,160.23
XS GIS Cut Line= 4
     3196231.807    13785145.642     3196099.755    13785324.551
     3196001.781    13785448.084     3195873.988    13785575.876
#Sta/Elev= 28
 4707.28   22.33 4708.23   22.33 4769.26   22.35 4779.92   22.39 4888.74   22.19
 4903.31   21.33    4918      20 4929.65   19.41 4962.38   11.63  4982.5     7.1
 4990.28    5.65 4992.06    4.94 4995.25    3.26 4999.88    5.07 5012.63    5.64
 5015.99    8.75  5041.1   15.72 5060.35   20.22 5071.96   20.67 5087.31   21.29
 5125.26   22.41 5138.65   22.38 5174.38   20.67 5190.01   20.28 5197.83   19.73
 5232.44   20.85 5241.82   20.88 5268.04   19.89
#Mann= 3 ,-1 , 0
 4707.28     .15       0 4929.65    .032       0 5060.35     .15       0
#XS Ineff= 2 , 0
       0    4988    19.5    5013       0    19.5
Permanent Ineff=
       F       F
Bank Sta=4929.65,5060.35
XS Rating Curve= 0
Exp/Cntr=0.5,0.3

Type RM Length L Ch R = 1 ,1162.439,555.74,606.01,654.37
XS GIS Cut Line= 4
      3196127.95    13785016.924     3195972.671    13785227.302
     3195882.138    13785341.452     3195776.002    13785447.588
#Sta/Elev= 28
 4675.67    20.7 4713.18   20.42 4716.16   20.29  4721.6   20.07 4751.57   18.27
 4774.77   18.43 4808.34   20.92 4810.28   21.06 4811.58   21.08 4813.43   21.05
 4887.59   20.92    4906      20    4946    16.9    4966   11.63  4977.5     7.1
 4985.28    5.65 4987.06    4.94 4990.25    3.26 4994.88    5.07 4997.95    5.59
    5005    8.75    5023   15.72    5045   20.22 5066.96   20.53 5082.84   21.08
 5112.81   22.92 5134.38   22.98 5232.94   22.81
#Mann= 3 ,-1 , 0
 4675.67     .15       0    4946    .032       0    5045     .15       0
Bank Sta=4946,5045
XS Rating Curve= 0
Exp/Cntr=0.3,0.1

Type RM Length L Ch R = 1 ,556.43  ,447.53,556.43,665.33
XS GIS Cut Line= 2
     3195925.728    13784630.111     3195298.116    13784908.658
#Sta/Elev= 25
 4621.66   21.24 4654.52   20.82 4706.43    20.5 4722.09   20.39 4733.97   19.74
 4753.63   18.22 4771.94   19.03 4839.05   20.76 4879.68   20.94 4901.17   20.75
 4903.95   20.39 4934.65   19.41 4967.38   11.63  4987.5     7.1 4995.28    5.65
 4997.06    4.94 5000.25    3.26 5004.88    5.07 5007.95    5.59 5020.99    8.75
  5046.1   15.72 5065.35   20.22 5076.96   20.67 5177.99   22.21 5308.31   21.74
#Mann= 3 ,-1 , 0
 4621.66     .15       0 4944.38    .032       0 5054.25     .15       0
Bank Sta=4934.65,5065.35
XS Rating Curve= 0
Exp/Cntr=0.3,0.1

Chan Stop Cuts=-1

--- B204_04_00.g02 (geometry) ---

Geom Title=B204-04-00 June 2007 (Floodway)
Program Version=3.11

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
River Reach=B204-04-00      ,B204-04-00_0006